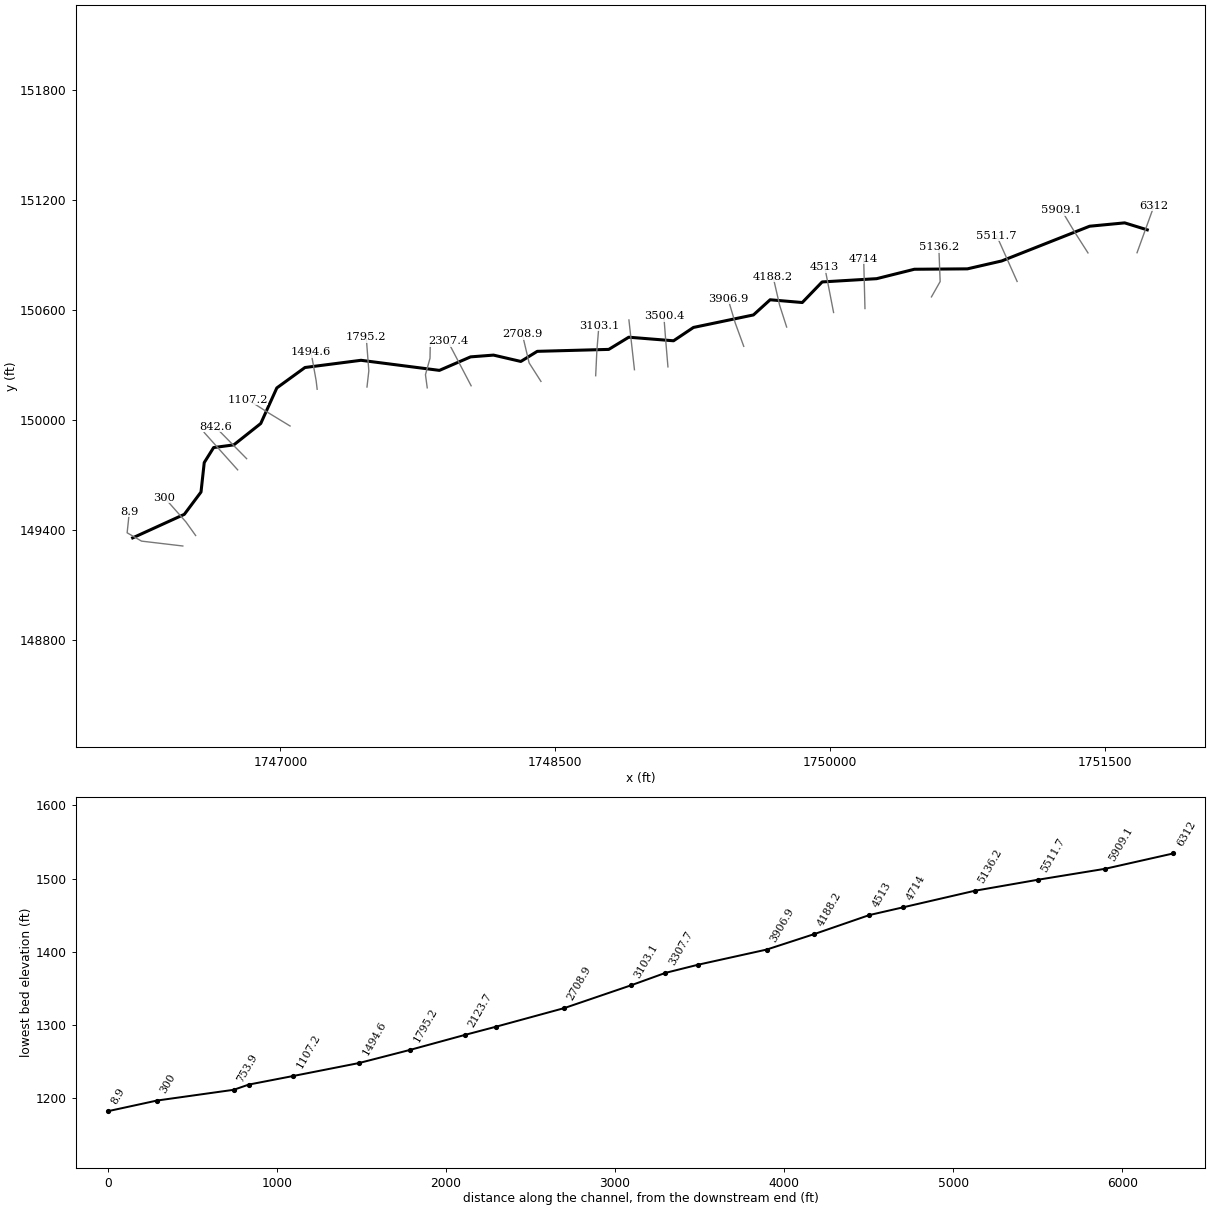
--- Left Fork Crane Creek.prj (project) ---

Proj Title=Left Fork Crane Creek
Current Plan=p01
Default Exp/Contr=0,0
English Units
Geom File=g01
Flow File=f01
Plan File=p01
BEGIN DESCRIPTION:
END DESCRIPTION:
DSS Export Rating Curves= 0
DSS Export Rating Curve Sorted= 0
DSS Export Volume Flow Curves= 0
DXF OffsetX= 0
DXF OffsetY= 0
DXF ScaleX= 0
DXF ScaleY= 0

--- Left Fork Crane Creek.p01 (plan) ---

Plan Title=Floodplain
Program Version=4.00
Geom File=g01
Flow File=f01
K Sum by GR=0
Std Step Tol=0.01
Critical Tol=0.01
Num of Std Step Trials=20
Max Error Tol=0.3
Flow Tol Ratio=0.001
Split Flow NTrial=30
Split Flow Tol=0.02
Split Flow Ratio=0.02
Log Output Level=0
Friction Slope Method=1
Unsteady Friction Slope Method=2
Unsteady Bridges Friction Slope Method=1
Global Log Level=0
CheckData=False
Run HTab=0
Run UNet=0
Run PostProcess=0
UNET Theta=0
UNET Theta Warmup=0
UNET ZTol=0
UNET ZSATol=0
UNET MxIter=0
UNET MaxInSteps=0
UNET DtIC=0
UNET DtMin=0
UNET MaxCRTS=0
UNET WFStab=0
UNET SFStab=0
UNET WFX=0
UNET SFX=0
UNET DSS MLevel=0
UNET DZMax Abort=0
UNET Convert EG Bridges=0
UNET Use Existing IB Tables=0
UNET Froude Limit=0
UNET Froude Power=0
Write IC File=0
Echo Input=False
Echo Output=False
Write Detailed=0

--- Left Fork Crane Creek.f01 (steady flow) ---

Flow Title=NFF Regression Equation
Program Version=4.00
Number of Profiles=1
Profile Names=P100yr
River Rch & RM=Left Fork Cra...,Main      ,6312
585.6295
River Rch & RM=Left Fork Cra...,Main      ,4188.2
634.9494
River Rch & RM=Left Fork Cra...,Main      ,1795.2
701.5105
River Rch & RM=Left Fork Cra...,Main      ,1494.6
873.1991
River Rch & RM=Left Fork Cra...,Main      ,300
892.3981
Boundary for River Rch & Prof#=Left Fork Cra...,Main      ,1
Up Type=0
Dn Type=3
Dn Slope=0.053388

--- Left Fork Crane Creek.g01 (geometry) ---

Geom Title=Geometry
Program Version=4.00

River Reach=Left Fork Cra...,Main
Reach XY= 30
     1751732.097      151037.207     1751608.637      151075.309
      1751417.43      151056.985      1750937.07      150867.285
     1750750.087      150824.275     1750460.634      150822.067
      1750254.81      150770.687     1749957.151      150752.844
     1749848.675      150640.461     1749673.151      150655.453
       1749582.1      150572.705     1749254.646      150504.375
     1749145.903      150431.566     1748901.457       150451.13
     1748792.306      150384.574     1748401.846      150373.925
       1748312.3      150318.762     1748163.112      150353.422
     1748038.009      150343.754     1747867.731      150270.028
     1747439.667      150325.068     1747133.839      150285.682
     1746980.218      150174.259     1746892.364      149979.916
     1746745.369      149863.342     1746635.104      149848.613
     1746583.944      149766.667     1746566.288      149605.943
     1746475.286      149484.155     1746193.267      149355.595

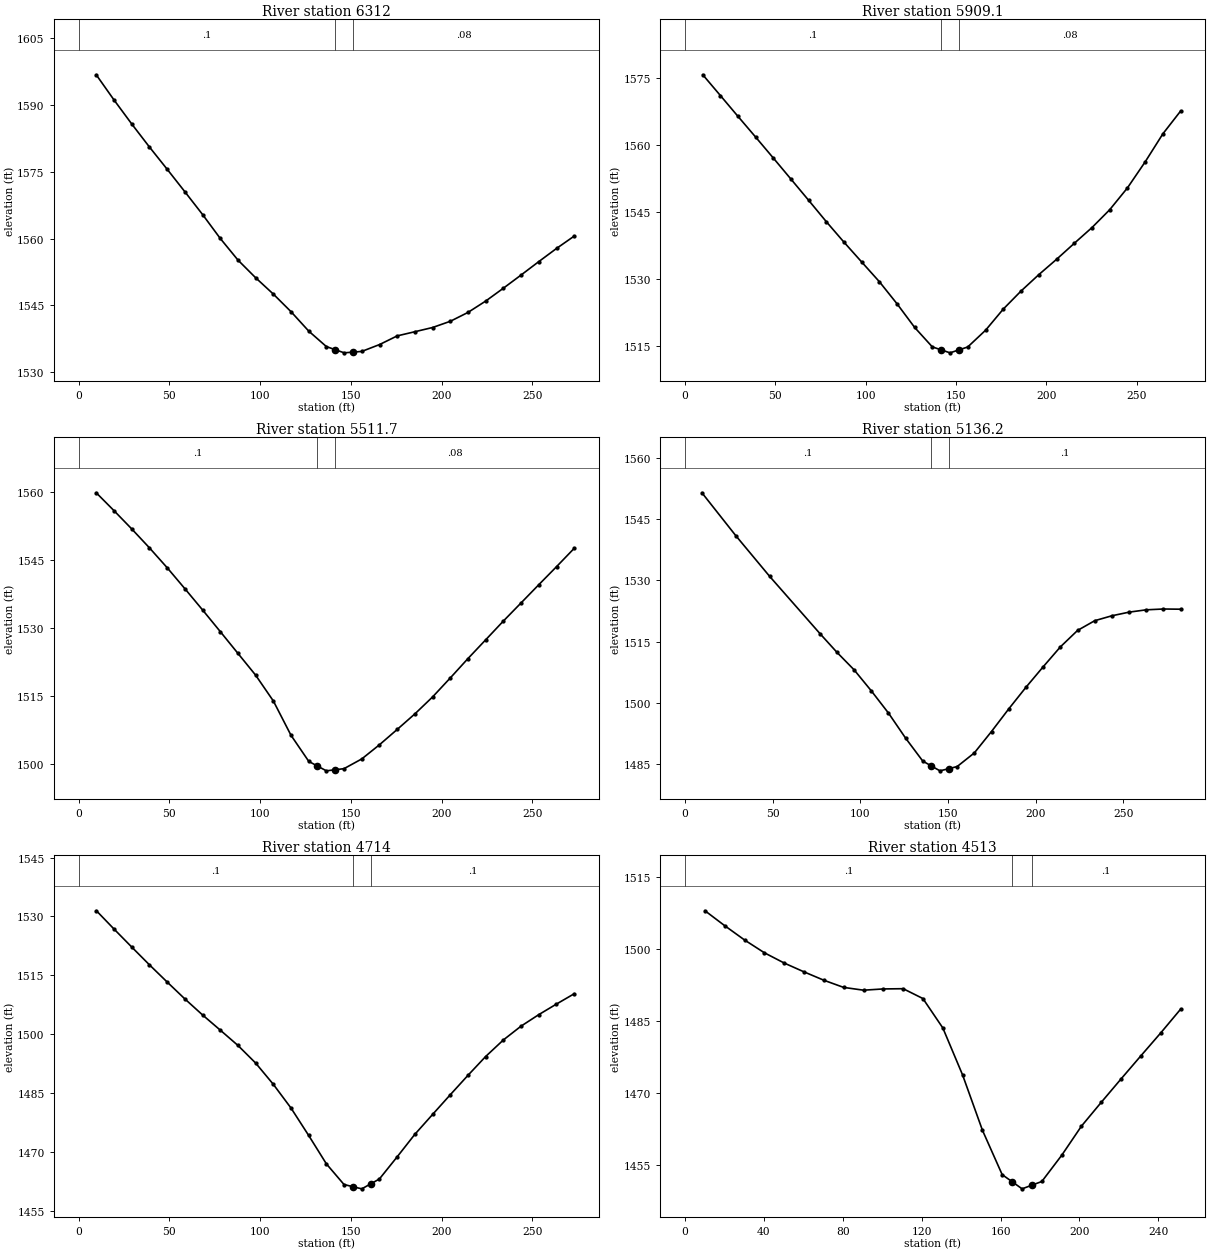
Type RM Length L Ch R = 1 ,6312    ,385.2,403,420.5
XS GIS Cut Line= 3
     1751676.215      150912.269     1751722.695      151040.612
     1751769.176      151168.955
#Sta/Elev= 30
     9.7 1596.71    19.5 1591.06    29.3 1585.66      39 1580.52    48.8 1575.52
    58.5  1570.5    68.3 1565.37      78 1560.03    87.8 1555.16    97.5 1551.21
   107.3 1547.53     117  1543.6   126.8 1539.23   136.5 1535.77   141.2  1535.1
   146.3 1534.37   151.2 1534.53     156 1534.69   165.8 1536.23   175.5 1538.17
   185.3 1539.11     195 1540.05   204.8 1541.45   214.5 1543.43   224.3 1545.99
     234 1548.86   243.8 1551.83   253.5 1554.82   263.3 1557.78     273 1560.54
#Mann= 3 , 0 , 0
       0      .1       0   141.2    .045       0   151.2     .08       0
Bank Sta=141.2,151.2
XS Rating Curve= 0 ,0
Exp/Cntr=0.3,0.1

Type RM Length L Ch R = 1 ,5909.1  ,400.2,397.4,394.9
XS GIS Cut Line= 3
     1751408.398      150911.341     1751334.562      151026.625
     1751263.899       151144.58
#Sta/Elev= 30
     9.8 1575.69    19.6 1571.01    29.3 1566.36    39.1 1561.71    48.9 1557.01
    58.7 1552.27    68.5 1547.52    78.2 1542.77      88 1538.17    97.8 1533.73
   107.6 1529.31   117.3  1524.4   127.1 1519.08   136.9 1514.71   141.7 1514.06
   146.7 1513.38   151.7 1514.05   156.5 1514.69   166.4 1518.45   176.2 1523.19
     186 1527.22   195.8 1530.88   205.7 1534.34   215.5 1537.92   225.3 1541.45
   235.1 1545.44   244.9 1550.32   254.8  1556.2   264.6 1562.48   274.4 1567.57
#Mann= 3 , 0 , 0
       0      .1       0   141.7    .045       0   151.7     .08       0
Bank Sta=141.7,151.7
XS Rating Curve= 0 ,0
Exp/Cntr=0.3,0.1

Type RM Length L Ch R = 1 ,5511.7  ,383.3,375.6,367.9
XS GIS Cut Line= 3
     1751021.496      150755.506     1750965.795      150880.125
     1750910.095      151004.743
#Sta/Elev= 30
     9.7 1559.73    19.5 1555.78    29.2 1551.78      39 1547.59    48.8 1543.19
    58.5 1538.59    68.3 1533.88      78 1529.13    87.7 1524.34    97.5 1519.51
   107.3 1513.79     117 1506.24   126.8 1500.48   131.5 1499.47   136.5  1498.4
   141.5 1498.65   146.2 1498.88     156 1501.03   165.7 1504.14   175.5 1507.53
   185.3 1510.98     195  1514.7   204.8 1518.91   214.5 1523.17   224.3 1527.32
     234 1531.44   243.8 1535.46   253.5 1539.45   263.3 1543.44     273 1547.47
#Mann= 3 , 0 , 0
       0      .1       0   131.5    .045       0   141.5     .08       0
Bank Sta=131.5,141.5
XS Rating Curve= 0 ,0
Exp/Cntr=0.3,0.1

Type RM Length L Ch R = 1 ,5136.2  ,422.4,422.2,422
XS GIS Cut Line= 3
      1750553.85      150671.135     1750601.399      150754.957
     1750594.152      150941.159
#Sta/Elev= 27
     9.6 1551.52    28.9    1541    48.2 1531.01    77.1 1516.86    86.7 1512.31
    96.4 1508.05   106.2  1502.9     116 1497.44   125.8 1491.27   135.6 1485.63
   140.4 1484.46   145.4 1483.24   150.4 1483.77   155.2 1484.29     165 1487.64
   174.8  1492.9   184.6 1498.43   194.4 1503.73   204.3  1508.8   214.1 1513.68
   223.9 1517.72   233.7 1520.11   243.5 1521.32   253.3 1522.21   263.1 1522.78
   272.9 1522.98   282.7 1522.93
#Mann= 3 , 0 , 0
       0      .1       0   140.4    .045       0   150.4      .1       0
Bank Sta=140.4,150.4
XS Rating Curve= 0 ,0
Exp/Cntr=0.3,0.1

Type RM Length L Ch R = 1 ,4714    ,197.7,201,204.3
XS GIS Cut Line= 3
     1750190.956      150607.573     1750187.396      150744.027
     1750183.836       150880.48
#Sta/Elev= 30
     9.8 1531.45    19.5  1526.8    29.3  1522.2      39  1517.7    48.8 1513.31
    58.5 1509.03    68.3 1504.93      78 1501.09    87.7 1497.21    97.5 1492.71
   107.2 1487.32     117 1481.25   126.7  1474.3   136.5 1467.04   146.2 1461.79
     151 1461.25     156 1460.69     161 1461.98   165.7  1463.2   175.5 1468.84
   185.2 1474.55     195 1479.62   204.7 1484.61   214.5 1489.58   224.2 1494.35
     234 1498.58   243.7 1502.08   253.5 1505.02   263.2  1507.7     273 1510.33
#Mann= 3 , 0 , 0
       0      .1       0     151    .045       0     161      .1       0
Bank Sta=151,161
XS Rating Curve= 0 ,0
Exp/Cntr=0.3,0.1

Type RM Length L Ch R = 1 ,4513    ,322.8,324.8,325.1
XS GIS Cut Line= 2
     1750019.592      150586.016     1749971.672      150832.716
#Sta/Elev= 27
    10.1 1507.98    20.1 1504.87    30.2 1501.88    40.2 1499.23    50.3 1497.08
    60.3 1495.25    70.4  1493.5    80.4 1492.01    90.5 1491.43   100.5 1491.69
   110.6 1491.74   120.6 1489.69   130.7 1483.56   140.7 1473.79   150.8 1462.23
   160.8 1452.99   165.9  1451.5   170.9 1450.03   175.9  1450.8   180.9 1451.56
     191 1457.03     201  1463.1   211.1 1468.09   221.2 1472.99   231.2 1477.78
   241.3 1482.57   251.3 1487.48
#Mann= 3 , 0 , 0
       0      .1       0   165.9    .045       0   175.9      .1       0
Bank Sta=165.9,175.9
XS Rating Curve= 0 ,0
Exp/Cntr=0.3,0.1

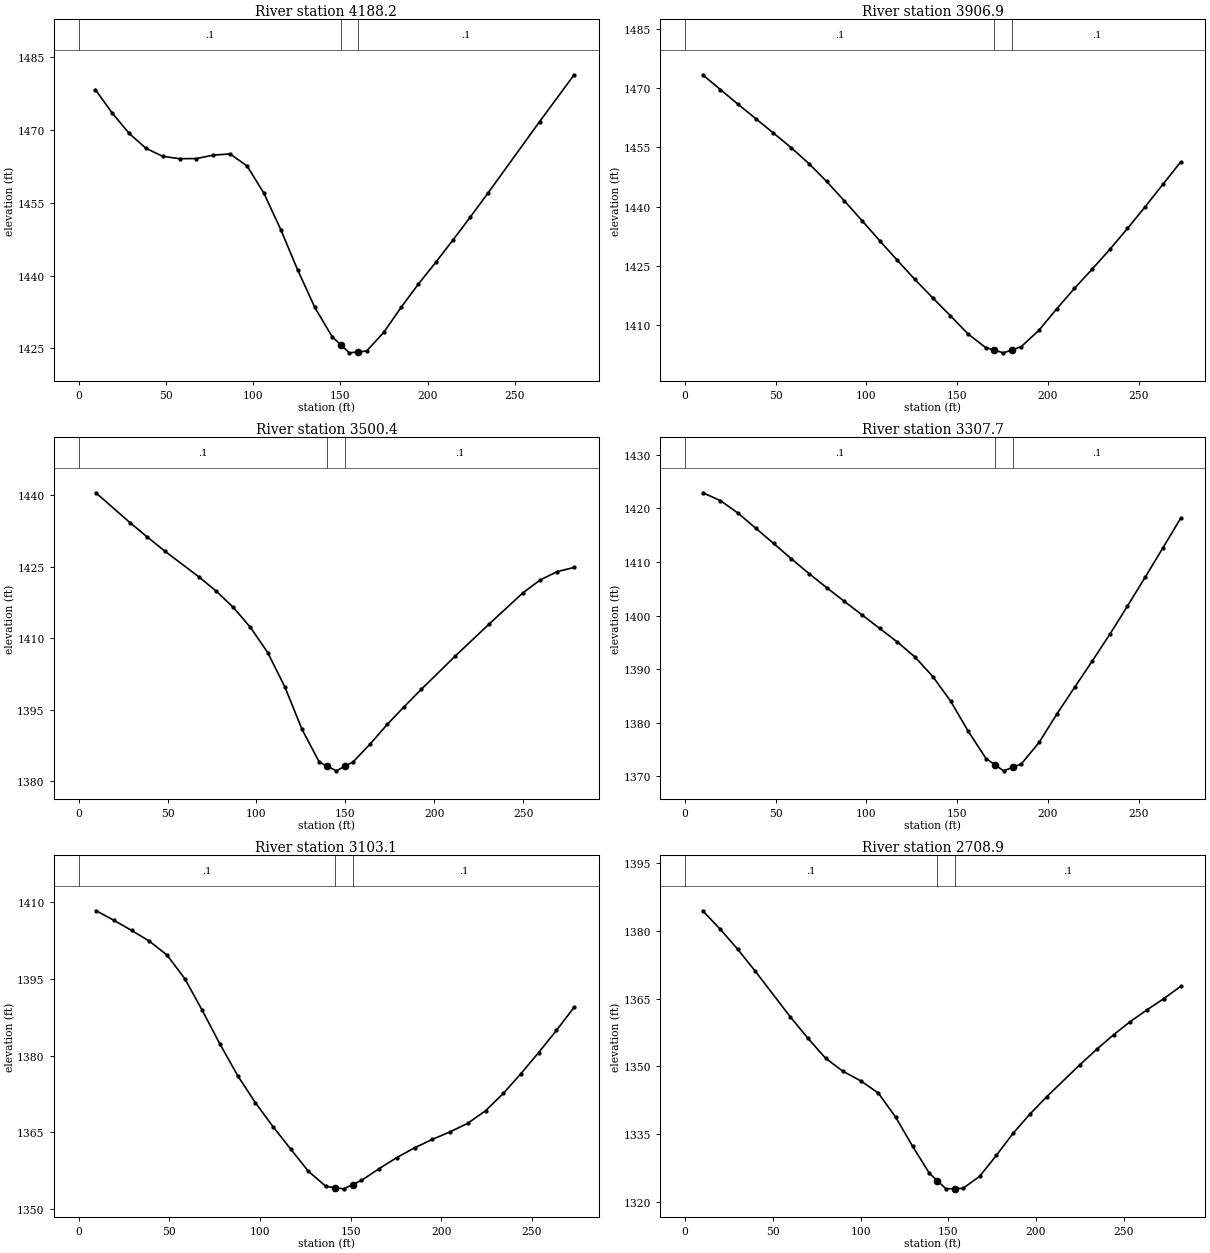
Type RM Length L Ch R = 1 ,4188.2  ,282.2,281.3,282.1
XS GIS Cut Line= 3
     1749763.377      150506.545     1749724.972       150625.95
     1749689.476      150780.359
#Sta/Elev= 28
     9.6 1478.24    19.3  1473.4    28.9 1469.25    38.6 1466.17    48.2 1464.52
    57.9 1464.04    67.5 1464.06    77.2 1464.78    86.8 1465.01    96.5 1462.53
   106.1 1456.97   115.8 1449.45   125.4 1441.22   135.3 1433.44   145.2 1427.43
   150.1 1425.77   155.1 1424.09   160.1 1424.28     165 1424.46   174.9 1428.34
   184.8 1433.48   194.7 1438.27   204.6 1442.71   214.5 1447.32   224.5 1452.08
   234.4  1456.9   264.1 1471.67   283.9  1481.3
#Mann= 3 , 0 , 0
       0      .1       0   150.1    .045       0   160.1      .1       0
Bank Sta=150.1,160.1
XS Rating Curve= 0 ,0
Exp/Cntr=0.3,0.1

Type RM Length L Ch R = 1 ,3906.9  ,411.2,406.5,401.7
XS GIS Cut Line= 3
     1749529.158      150401.267     1749482.477      150529.483
     1749443.258      150660.523
#Sta/Elev= 30
     9.7 1473.41    19.5 1469.65    29.2 1465.94      39 1462.27    48.7 1458.64
    58.5 1454.94    68.2 1450.91      78 1446.39    87.7  1441.5    97.5 1436.46
   107.2 1431.39     117 1426.38   126.7 1421.52   136.5 1416.86   146.2 1412.36
     156  1407.7   165.8 1404.22   170.5 1403.59   175.5 1402.92   180.5 1403.71
   185.3 1404.48   195.1 1408.65   204.8 1414.03   214.6 1419.24   224.4 1424.12
   234.2 1429.17   243.9 1434.45   253.7 1439.99   263.5 1445.68   273.2  1451.3
#Mann= 3 , 0 , 0
       0      .1       0   170.5    .045       0   180.5      .1       0
Bank Sta=170.5,180.5
XS Rating Curve= 0 ,0
Exp/Cntr=0.3,0.1

Type RM Length L Ch R = 1 ,3500.4  ,192.1,192.7,193.3
XS GIS Cut Line= 3
     1749115.348      150289.115     1749104.008      150423.948
     1749092.883      150566.762
#Sta/Elev= 26
     9.7 1440.52      29 1434.21    38.7 1431.21    48.3 1428.32    67.7 1422.84
    77.3 1419.89      87 1416.44    96.6 1412.27   106.3 1406.98     116 1399.72
   125.6 1390.85   135.3 1383.98   139.9  1383.1   144.9 1382.15   149.9 1383.15
   154.4 1384.05     164 1387.83   173.5 1391.89   183.1 1395.65   192.6 1399.24
   211.7 1406.23   230.8 1412.97   249.9 1419.55   259.5 1422.22     269 1423.96
   278.6 1424.85
#Mann= 3 , 0 , 0
       0      .1       0   139.9    .045       0   149.9      .1       0
Bank Sta=139.9,149.9
XS Rating Curve= 0 ,0
Exp/Cntr=0.3,0.1

Type RM Length L Ch R = 1 ,3307.7  ,207.9,204.6,200.8
XS GIS Cut Line= 2
     1748932.517      150273.648     1748902.345      150545.195
#Sta/Elev= 30
     9.8 1422.92    19.5 1421.45    29.3 1419.09      39 1416.28    48.8 1413.46
    58.5 1410.62    68.3 1407.84    78.1  1405.2    87.8 1402.65    97.6 1400.11
   107.3 1397.59   117.1 1395.04   126.9 1392.21   136.6  1388.6   146.4 1384.02
   156.1  1378.4   165.9 1373.31   170.6 1372.19   175.6 1371.01   180.6 1371.67
   185.4 1372.31   195.2 1376.33   204.9 1381.58   214.7 1386.58   224.4 1391.46
   234.2 1396.53   243.9 1401.78   253.7 1407.19   263.5 1412.68   273.2 1418.15
#Mann= 3 , 0 , 0
       0      .1       0   170.6    .045       0   180.6      .1       0
Bank Sta=170.6,180.6
XS Rating Curve= 0 ,0
Exp/Cntr=0.3,0.1

Type RM Length L Ch R = 1 ,3103.1  ,388.8,394.2,400.1
XS GIS Cut Line= 3
     1748720.833      150240.835     1748727.324      150377.127
     1748738.411      150513.518
#Sta/Elev= 30
     9.7 1408.33    19.5 1406.45    29.2 1404.49      39 1402.39    48.7 1399.68
    58.5 1395.08    68.2 1388.83      78 1382.21    87.7 1376.09    97.5 1370.77
   107.2  1366.1     117 1361.69   126.7 1357.37   136.4  1354.4   141.2 1354.17
   146.2 1353.93   151.2 1354.77     156 1355.58   165.8 1357.89   175.5 1360.05
   185.3 1361.96   195.1 1363.61   204.9 1365.09   214.6 1366.75   224.4  1369.2
   234.2 1372.59     244 1376.49   253.7 1380.59   263.5 1384.92   273.3 1389.47
#Mann= 3 , 0 , 0
       0      .1       0   141.2    .045       0   151.2      .1       0
Bank Sta=141.2,151.2
XS Rating Curve= 0 ,0
Exp/Cntr=0.3,0.1

Type RM Length L Ch R = 1 ,2708.9  ,398,401.5,406.8
XS GIS Cut Line= 3
      1748422.15      150209.734     1748357.476      150310.919
     1748320.205      150468.878
#Sta/Elev= 29
      10 1384.47      20  1380.4      30 1375.93      40 1371.07      60 1360.93
    70.1 1356.17    80.1 1351.77    90.1 1348.86   100.1 1346.77   110.1 1344.07
   120.1 1338.67   129.6  1332.3   139.2  1326.3   143.7 1324.66   148.7 1322.84
   153.7 1322.89   158.3 1322.94   167.8 1325.58   177.4 1330.26   186.9 1335.14
   196.5  1339.4     206 1343.23   225.1 1350.39   234.7 1353.81   244.2 1356.99
   253.7 1359.91   263.3 1362.53   272.8 1364.99   282.4 1367.72
#Mann= 3 , 0 , 0
       0      .1       0   143.7    .045       0   153.7      .1       0
Bank Sta=143.7,153.7
XS Rating Curve= 0 ,0
Exp/Cntr=0.3,0.1

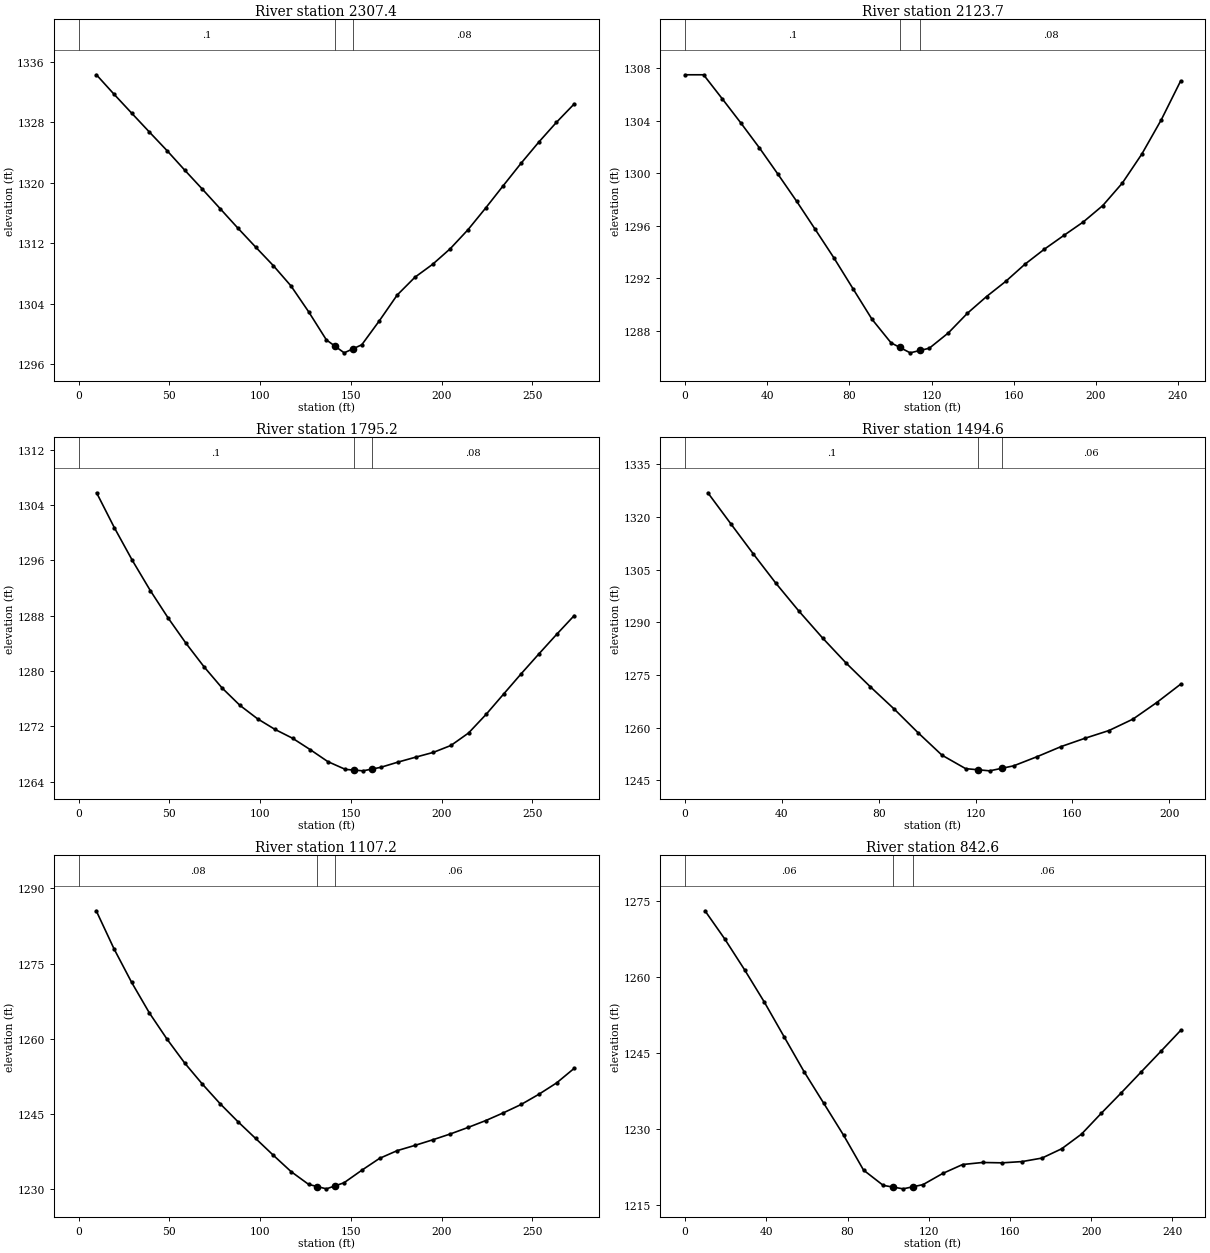
Type RM Length L Ch R = 1 ,2307.4  ,199,183.7,168.3
XS GIS Cut Line= 3
     1748040.901      150185.978     1747977.563      150306.893
     1747914.225      150427.809
#Sta/Elev= 30
     9.8 1334.31    19.5 1331.74    29.2 1329.24      39 1326.73    48.8 1324.25
    58.5 1321.68    68.2 1319.17      78 1316.59    87.7 1314.03    97.5 1311.52
   107.3 1309.05     117 1306.37   126.7 1302.96   136.5 1299.23   141.2 1298.41
   146.3 1297.52   151.2 1298.06     156 1298.59   165.7 1301.77   175.5 1305.17
   185.3 1307.53     195 1309.23   204.7 1311.29   214.5 1313.81   224.2 1316.67
     234 1319.66   243.8 1322.62   253.5  1325.4   263.2 1328.01     273 1330.45
#Mann= 3 , 0 , 0
       0      .1       0   141.2    .045       0   151.2     .08       0
Bank Sta=141.2,151.2
XS Rating Curve= 0 ,0
Exp/Cntr=0.3,0.1

Type RM Length L Ch R = 1 ,2123.7  ,321.4,328.5,335.6
XS GIS Cut Line= 4
     1747801.275       150174.73     1747791.617      150246.475
     1747816.452      150336.156     1747817.832       150412.04
#Sta/Elev= 29
       0  1307.5       9  1307.5    18.1 1305.67    27.1 1303.84    36.2 1301.93
    45.2 1299.93    54.3 1297.87    63.3 1295.74    72.4 1293.57    81.7 1291.22
      91 1288.88   100.3 1287.08   104.6 1286.73   109.6 1286.32   114.6 1286.51
   118.9 1286.67   128.2 1287.84   137.5 1289.34   146.8 1290.61   156.1 1291.76
   165.4 1293.06   174.9 1294.21   184.4 1295.26   193.9 1296.29   203.4 1297.54
   212.9 1299.25   222.4 1301.46   231.9 1304.08   241.3 1307.03
#Mann= 3 , 0 , 0
       0      .1       0   104.6    .045       0   114.6     .08       0
Bank Sta=104.6,114.6
XS Rating Curve= 0 ,0
Exp/Cntr=0.3,0.1

Type RM Length L Ch R = 1 ,1795.2  ,298.7,300.6,302.6
XS GIS Cut Line= 3
      1747472.38      150179.158     1747482.491      150267.436
     1747468.292       150451.13
#Sta/Elev= 30
     9.9 1305.76    19.7 1300.71    29.6 1295.99    39.5 1291.63    49.4 1287.64
    59.2    1284    69.1 1280.62      79 1277.57    88.9 1275.04    98.6  1273.1
   108.2 1271.57   117.9 1270.29   127.6 1268.65   137.3 1266.92     147 1265.79
   151.7 1265.69   156.7 1265.58   161.7 1265.84   166.4 1266.08   176.1 1266.85
   185.8 1267.56   195.5 1268.25   205.2 1269.25   214.9 1271.05   224.6 1273.75
   234.3  1276.7     244 1279.64   253.7 1282.49   263.4 1285.29   273.1 1288.01
#Mann= 3 , 0 , 0
       0      .1       0   151.7    .045       0   161.7     .08       0
Bank Sta=151.7,161.7
XS Rating Curve= 0 ,0
Exp/Cntr=0.3,0.1

Type RM Length L Ch R = 1 ,1494.6  ,370.3,387.4,404
XS GIS Cut Line= 3
     1747200.406      150167.048      1747194.86      150213.637
     1747167.128      150368.934
#Sta/Elev= 23
     9.4 1326.89    18.8 1318.14    28.2 1309.46    37.5 1301.13    46.9 1293.28
    56.8 1285.53    66.6 1278.33    76.5 1271.65    86.4 1265.28    96.2 1258.58
   106.1 1252.17   115.9 1248.32   120.8 1248.02   125.8  1247.7   130.8 1248.42
   135.7 1249.12   145.5 1251.76   155.4 1254.63   165.2 1256.98   175.1 1259.18
     185 1262.43   194.8 1267.14   204.7 1272.38
#Mann= 3 , 0 , 0
       0      .1       0   120.8    .045       0   130.8     .06       0
Bank Sta=120.8,130.8
XS Rating Curve= 0 ,0
Exp/Cntr=0.3,0.1

Type RM Length L Ch R = 1 ,1107.2  ,268.7,264.6,262.2
XS GIS Cut Line= 3
     1747052.432        149966.4     1746935.846      150037.378
     1746820.868      150111.026
#Sta/Elev= 30
     9.7 1285.53    19.5 1277.94    29.2 1271.25      39 1265.14    48.7 1259.93
    58.5 1255.13    68.2 1250.95      78 1247.03    87.7 1243.49    97.5 1240.12
   107.2 1236.79     117 1233.52   126.7 1230.96   131.5 1230.52   136.5 1230.07
   141.5 1230.69   146.2 1231.28     156 1233.78   165.8 1236.15   175.5 1237.69
   185.3 1238.74     195 1239.84   204.8 1241.02   214.5 1242.31   224.3 1243.69
     234 1245.23   243.8  1246.9   253.5 1248.92   263.3 1251.19     273  1254.1
#Mann= 3 , 0 , 0
       0     .08       0   131.5    .045       0   141.5     .06       0
Bank Sta=131.5,141.5
XS Rating Curve= 0 ,0
Exp/Cntr=0.3,0.1

Type RM Length L Ch R = 1 ,842.6   ,88.9,88.7,86.2
XS GIS Cut Line= 2
     1746815.377      149787.971     1746644.107      149961.903
#Sta/Elev= 27
     9.8    1273    19.5 1267.47    29.3 1261.38    39.1 1254.97    48.8 1248.17
    58.6 1241.32    68.3 1235.09    78.1 1228.78    87.9 1221.93    97.6 1218.92
   102.4 1218.59   107.4 1218.24   112.4 1218.66   117.2 1219.07   126.9 1221.27
   136.7 1223.03   146.5 1223.43   156.2 1223.36     166 1223.61   175.8  1224.3
   185.5 1226.13   195.3 1229.03     205 1233.12   214.8 1237.13   224.6 1241.24
   234.3  1245.3   244.1 1249.44
#Mann= 3 , 0 , 0
       0     .06       0   102.4    .045       0   112.4     .06       0
Bank Sta=102.4,112.4
XS Rating Curve= 0 ,0
Exp/Cntr=0.3,0.1

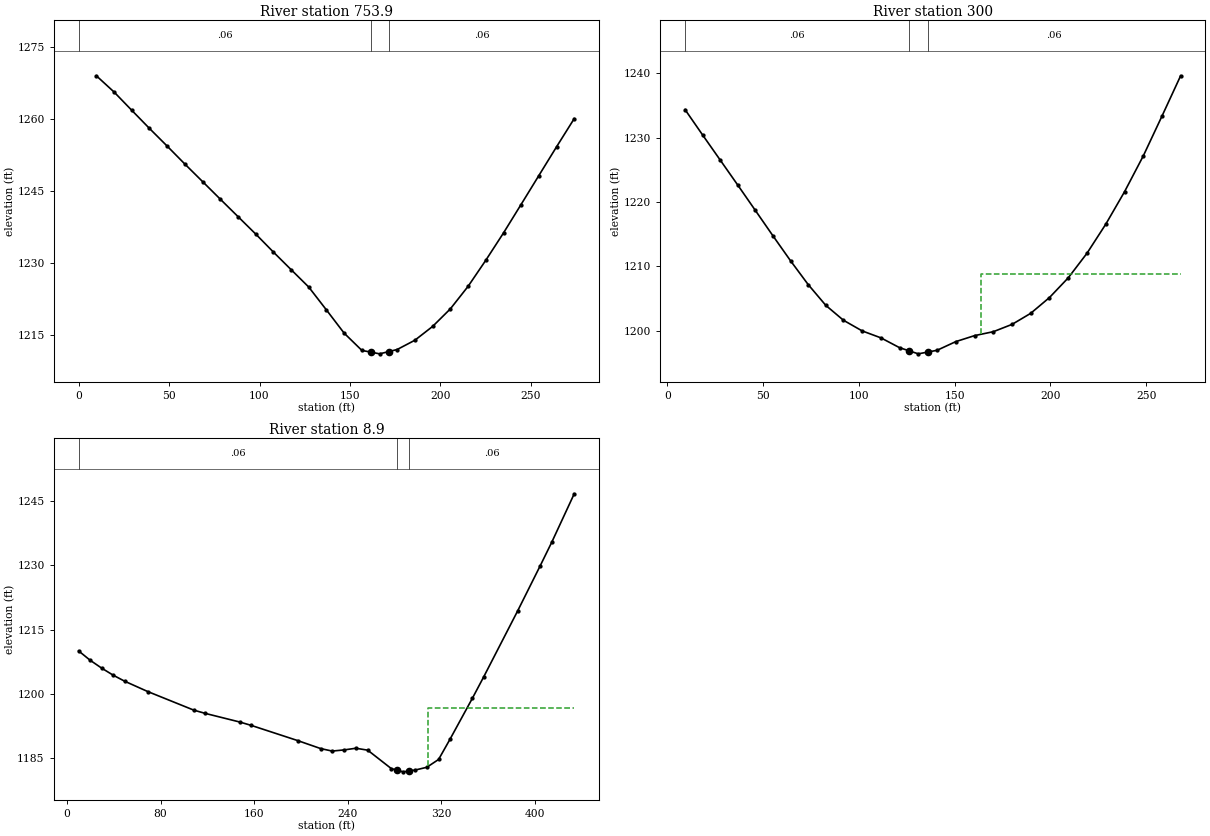
Type RM Length L Ch R = 1 ,753.9   ,455.1,454,453.6
XS GIS Cut Line= 2
     1746766.352      149727.005     1746583.546      149931.109
#Sta/Elev= 30
     9.8 1268.97    19.6 1265.59    29.4 1261.78    39.1 1258.04    48.9 1254.36
    58.7 1250.62    68.5 1246.97    78.3 1243.31    88.1 1239.68    97.9 1236.05
   107.6 1232.33   117.4 1228.67   127.2 1225.03     137 1220.26   146.8 1215.43
   156.6 1211.84   161.4  1211.5   166.4 1211.13   171.4 1211.59   176.1 1212.03
   185.9 1213.96   195.7 1216.83   205.5 1220.48   215.3 1225.16   225.1 1230.59
   234.9 1236.28   244.6 1242.19   254.4 1248.19   264.2 1254.18     274 1260.06
#Mann= 3 , 0 , 0
       0     .06       0   161.4    .045       0   171.4     .06       0
Bank Sta=161.4,171.4
XS Rating Curve= 0 ,0
Exp/Cntr=0.3,0.1

Type RM Length L Ch R = 1 ,300     ,284,291,298
XS GIS Cut Line= 3
     1746537.001       149368.52     1746483.495       149443.22
     1746366.846      149575.195
#Sta/Elev= 30
     9.2 1234.35    18.4  1230.4    27.6  1226.5    36.8  1222.6    45.9  1218.7
    55.1 1214.75    64.3 1210.87    73.5 1207.18    82.7 1203.95    91.9 1201.64
   101.7 1199.98   111.5  1198.9   121.2 1197.38     126 1196.91     131 1196.42
     136  1196.7   140.8 1196.97   150.6 1198.32   160.4 1199.25   170.2 1199.86
     180    1201   189.7 1202.71   199.5 1205.16   209.3 1208.22   219.1 1212.04
   228.9 1216.55   238.7 1221.59   248.5 1227.16   258.2  1233.3     268  1239.6
#Mann= 3 , 0 , 0
     9.2     .06       0     126    .045       0     136     .06       0
#XS Ineff= 2 , 0
                          163.59         1208.82
Permanent Ineff=
       F       F
Bank Sta=126,136
XS Rating Curve= 0 ,0
Exp/Cntr=0.3,0.1

Type RM Length L Ch R = 1 ,8.9     ,8.7,8.9,9.2
XS GIS Cut Line= 4
     1746466.969      149311.283     1746241.789      149337.905
     1746163.032      149383.385     1746175.234      149498.748
#Sta/Elev= 30
     9.9 1210.05    19.7 1207.88    29.6 1206.03    39.4 1204.39    49.3 1202.97
      69 1200.56   108.4 1196.22   118.3 1195.45   147.9 1193.43   157.7 1192.64
   197.2 1189.11   216.9 1187.24   226.7 1186.66   236.9 1186.93     247 1187.32
   257.1 1186.87   277.3 1182.56   282.4 1182.18   287.4 1181.81   292.4 1182.01
   297.5 1182.22   307.6 1182.87   317.7  1184.7   327.4 1189.39   346.7 1199.04
   356.4 1204.05   385.4 1219.44   404.7 1229.99   414.4 1235.39   433.7 1246.75
#Mann= 3 , 0 , 0
     9.9     .06       0   282.4    .045       0   292.4     .06       0
#XS Ineff= 2 , 0
                          308.72         1196.79
Permanent Ineff=
       F       F
Bank Sta=282.4,292.4
XS Rating Curve= 0 ,0
Exp/Cntr=0.3,0.1
Stream Node=Left Fork Cra...,Main            , 0 , 0 ,Upstream end
Stream Node=Left Fork Cra...,Main            , 0 , 1 ,Downstream end

Chan Stop Cuts=-1
Use User Specified Reach Order=0